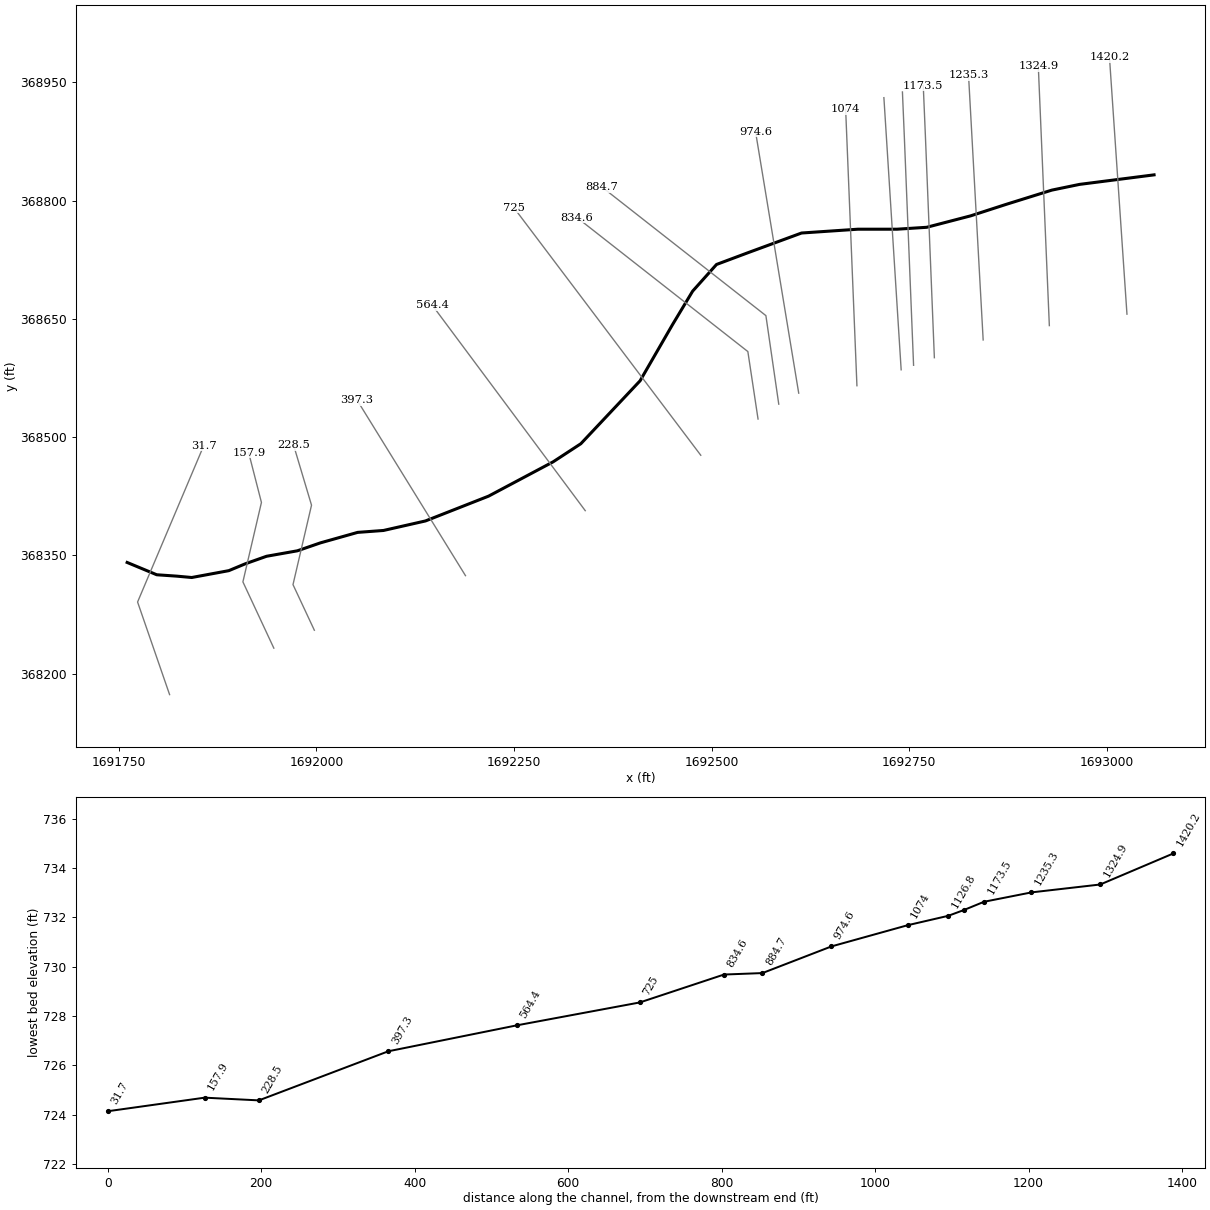
--- NFBIGCK.prj (project) ---

Proj Title=NFBIGCK
Current Plan=p01
Default Exp/Contr=0,0
English Units
Geom File=g01
Flow File=f01
Plan File=p01
BEGIN DESCRIPTION:
END DESCRIPTION:
DSS Export Rating Curves= 0
DSS Export Rating Curve Sorted= 0
DSS Export Volume Flow Curves= 0
DXF OffsetX= 0
DXF OffsetY= 0
DXF ScaleX= 0
DXF ScaleY= 0

--- NFBIGCK.p01 (plan) ---

Plan Title=Floodplain
Program Version=4.00
Geom File=g01
Flow File=f01
K Sum by GR=0
Std Step Tol=0.01
Critical Tol=0.01
Num of Std Step Trials=20
Max Error Tol=0.3
Flow Tol Ratio=0.001
Split Flow NTrial=30
Split Flow Tol=0.02
Split Flow Ratio=0.02
Log Output Level=0
Friction Slope Method=1
Unsteady Friction Slope Method=2
Unsteady Bridges Friction Slope Method=1
Global Log Level=0
CheckData=False
Run HTab=0
Run UNet=0
Run PostProcess=0
UNET Theta=0
UNET Theta Warmup=0
UNET ZTol=0
UNET ZSATol=0
UNET MxIter=0
UNET MaxInSteps=0
UNET DtIC=0
UNET DtMin=0
UNET MaxCRTS=0
UNET WFStab=0
UNET SFStab=0
UNET WFX=0
UNET SFX=0
UNET DSS MLevel=0
UNET DZMax Abort=0
UNET Convert EG Bridges=0
UNET Use Existing IB Tables=0
UNET Froude Limit=0
UNET Froude Power=0
Write IC File=0
Echo Input=False
Echo Output=False
Write Detailed=0

--- NFBIGCK.f01 (steady flow) ---

Flow Title=NFF Regression Equation
Program Version=4.10
Number of Profiles= 1
Profile Names=P100yr
River Rch & RM=NFBIGCK,Main            ,1420.2
1223.213
River Rch & RM=NFBIGCK,Main            ,397.3
1237.166
Boundary for River Rch & Prof#=NFBIGCK,Main            , 1
Up Type= 0
Dn Type= 3
Dn Slope=0.004881
DSS Import GetInterval= 0
DSS Import GetPeak= 0
DSS Import FillOption= 0

--- NFBIGCK.g01 (geometry) ---

Geom Title=USGS 10m DEM
Program Version=5.03

River Reach=NFBIGCK         ,Main
Reach XY= 29
     1693059.751      368832.508     1692965.479      368820.423
      1692930.43      368813.171     1692872.417      368795.042
     1692827.698      368780.539     1692772.102      368766.035
     1692734.635      368763.618     1692685.083      368763.618
     1692613.775      368758.784     1692544.884      368733.403
     1692506.208        368718.9     1692475.993      368685.058
     1692450.613      368642.757      1692409.52       368571.45
     1692334.586      368491.681     1692299.537      368468.718
     1692217.834      368425.208     1692138.066      368393.784
     1692084.888      368381.698     1692052.255      368379.281
      1692005.12      368365.986     1691976.017      368355.929
     1691936.954      368348.984     1691910.044      368339.436
     1691889.211      368330.755     1691842.336      368322.074
     1691823.239       368323.81     1691798.065      368325.547
     1691760.602      368341.156

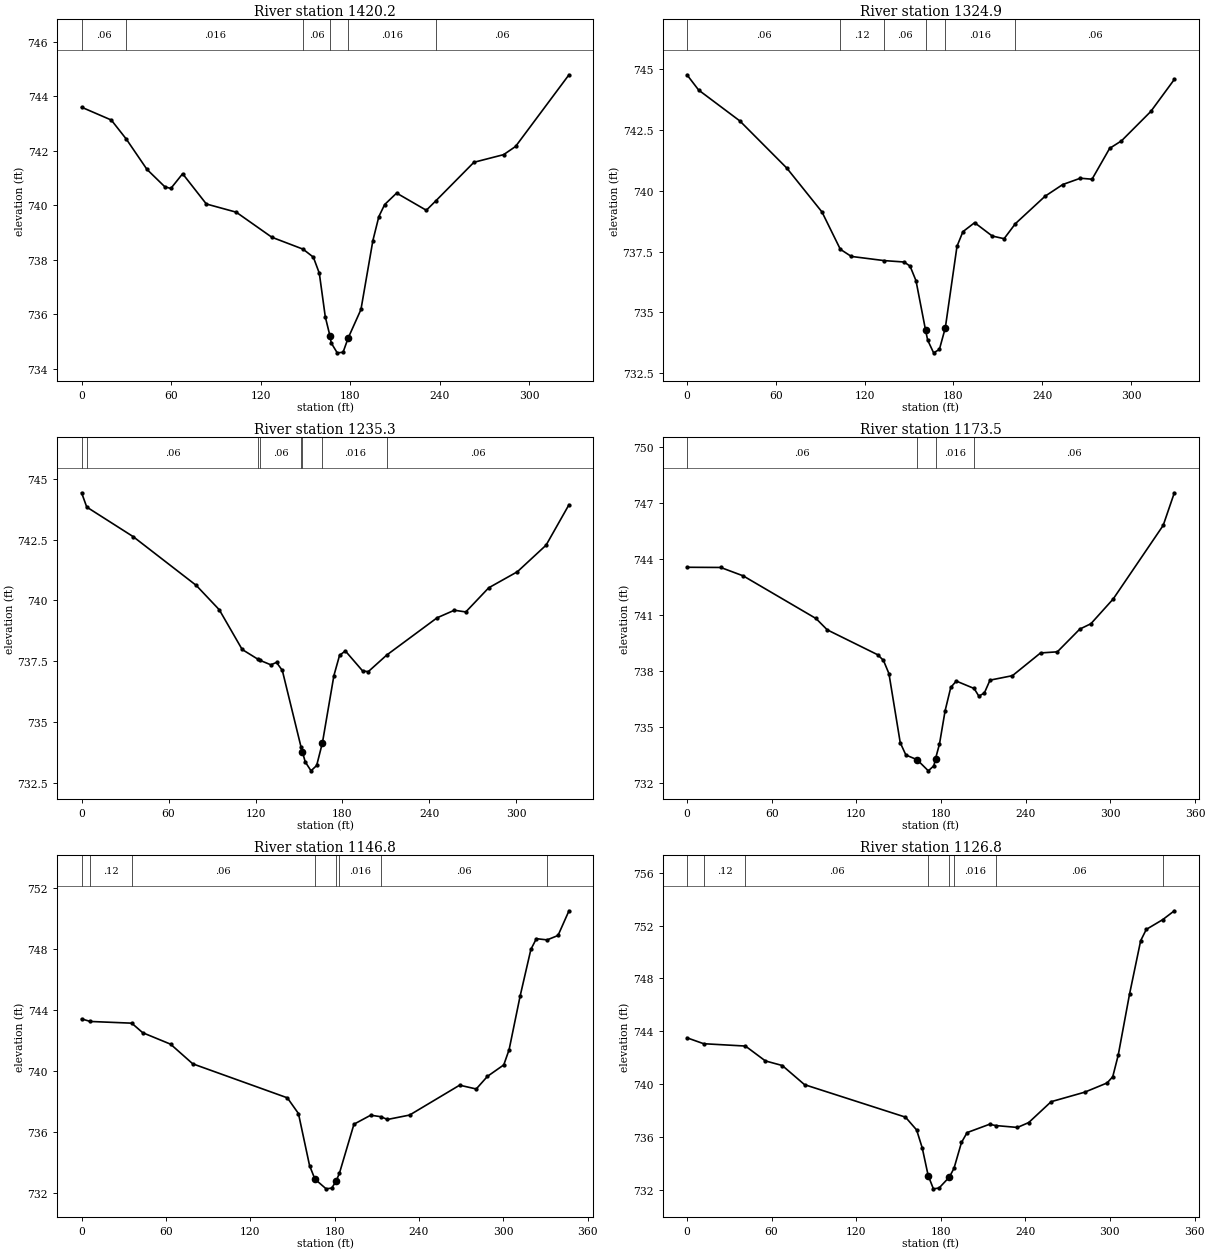
Type RM Length L Ch R = 1 ,1420.2  ,95.9,95.4,94.5
XS GIS Cut Line= 2
     1693025.461      368655.919     1693003.304      368981.778
#Sta/Elev= 30
       0   743.6    19.9  743.13   29.97742.4296    43.8  741.32    55.8  740.68
    59.8  740.62    67.7  741.16    83.6  740.05   103.6  739.75   127.5  738.83
  148.38738.3937   155.3   738.1   159.3  737.51   163.3  735.91  166.39  735.22
   167.3  734.95   171.3  734.59   175.2  734.61   178.6  735.13   187.2  736.18
   195.2  738.71   199.2  739.59   203.1  740.03   211.1  740.45     231  739.82
  237.19740.1552   262.9  741.58   282.8  741.86   290.8  742.16   326.6  744.79
#Mann= 6 ,-1 , 0
       0     .06       0   29.97    .016       0  148.38     .06       0
  166.39    .045       0   178.6    .016       0  237.19     .06       0
Bank Sta=166.39,178.6
XS Rating Curve= 0 ,0
Exp/Cntr=0.3,0.1

Type RM Length L Ch R = 1 ,1324.9  ,88.9,89.6,89.5
XS GIS Cut Line= 2
     1692927.261      368641.403     1692913.291      368970.273
#Sta/Elev= 30
       0  744.78     7.9  744.15    35.7  742.88    67.4  740.94    91.2  739.13
  103.58737.5948     111   737.3  133.14737.1283   146.7  737.07   150.7   736.9
   154.7   736.3   161.2  734.25   162.6  733.85   166.6  733.33   170.5  733.47
   174.5  734.36   182.4  737.72   186.4  738.32   194.3  738.69   206.2  738.14
   214.2  738.03  221.83 738.649   241.9  739.78   253.8  740.26   265.7  740.52
   273.6  740.48   285.5  741.75   293.5  742.06   313.3  743.27   329.2  744.59
#Mann= 6 ,-1 , 0
       0     .06       0  103.58     .12       0  133.14     .06       0
   161.2    .045       0   174.5    .016       0  221.83     .06       0
Bank Sta=161.2,174.5
XS Rating Curve= 0 ,0
Exp/Cntr=0.3,0.1

Type RM Length L Ch R = 1 ,1235.3  ,62.5,61.8,61.8
XS GIS Cut Line= 2
     1692843.547      368623.207     1692825.025      368958.991
#Sta/Elev= 30
       0  744.42    3.55743.8342    35.6  742.62    79.1  740.62      95  739.62
   110.8  737.99  121.87737.5825   123.1 737.545   130.6  737.36   134.5  737.46
   138.5  737.13  151.45733.9791   152.4  733.78   154.3  733.38   158.3  733.01
   162.2  733.23   166.2  734.17   174.1  736.92     178  737.75     182  737.93
   193.9  737.11   197.8  737.08  210.61737.7643   245.3  739.29   257.2   739.6
   265.1  739.53   280.9  740.52   300.7  741.18   320.5  742.27   336.3  743.93
#Mann= 8 ,-1 , 0
       0     .12       0    3.55     .06       0  121.87     .12       0
   123.1     .06       0  151.45    .016       0   152.4    .045       0
   166.2    .016       0  210.61     .06       0
Bank Sta=152.4,166.2
XS Rating Curve= 0 ,0
Exp/Cntr=0.3,0.1

Type RM Length L Ch R = 1 ,1173.5  ,26.7,26.7,26.9
XS GIS Cut Line= 3
     1692781.808      368600.704     1692770.425      368882.769
     1692767.757      368945.697
#Sta/Elev= 30
       0  743.56    23.9  743.55    39.8   743.1    91.4  740.81    99.4   740.2
   135.2  738.86   139.2  738.56   143.1  737.85   151.1  734.14   155.1  733.48
     163  733.23     171  732.63   174.9   732.9  176.09  733.28   178.9  734.07
   182.9  735.86   186.9  737.11   190.8  737.45  203.43737.0529   206.8  736.64
   210.7  736.81   214.7   737.5   230.6  737.74   250.5  738.96   262.4  739.02
   278.3  740.24   286.2  740.53     302  741.86   337.4  745.81   345.3  747.56
#Mann= 4 ,-1 , 0
       0     .06       0     163    .045       0  176.09    .016       0
  203.43     .06       0
Bank Sta=163,176.09
XS Rating Curve= 0 ,0
Exp/Cntr=0.3,0.1

Type RM Length L Ch R = 1 ,1146.8  ,19.5,20,20.5
XS GIS Cut Line= 3
     1692755.506      368591.117     1692743.863      368879.644
     1692741.406      368937.589
#Sta/Elev= 30
       0  743.44    6.11743.2697   35.67743.1573    43.5  742.53    63.3  741.78
    79.1  740.49   146.4  738.26   154.3  737.23   162.2  733.82     166  732.93
     174  732.29     178  732.34     181  732.78  183.46 733.313   193.8  736.53
   205.7  737.12  213.02737.0203   217.6  736.84   233.4  737.13     269  739.09
   280.8  738.84   288.8  739.67   300.4  740.42   304.2  741.42     312  744.92
   319.7     748   323.6   748.7  331.26748.6204     339  748.91   346.8  750.53
#Mann= 8 ,-1 , 0
       0     .06       0    6.11     .12       0   35.67     .06       0
     166    .045       0     181     .06       0  183.46    .016       0
  213.02     .06       0  331.26     .12       0
Bank Sta=166,181
XS Rating Curve= 0 ,0
Exp/Cntr=0.3,0.1

Type RM Length L Ch R = 1 ,1126.8  ,53.2,52.8,52.2
XS GIS Cut Line= 2
     1692739.803      368585.394     1692717.961      368930.375
#Sta/Elev= 30
       0   743.5   11.85743.0513   41.45742.8744    55.6  741.75    67.6   741.4
    83.4  739.95     155  737.49   162.9  736.52   166.9  735.15   171.1  733.06
   174.8  732.06   178.8  732.12   186.1  732.95  189.42733.6184   194.7  735.57
   198.7  736.32   214.6  736.95  219.01736.8532   234.4  736.71   242.4  737.08
   258.3  738.66   282.1  739.38     298  740.08     302  740.55   305.9  742.19
   313.9   746.8   321.8  750.85   325.8  751.71  337.39752.4449   345.7  753.12
#Mann= 8 ,-1 , 0
       0     .06       0   11.85     .12       0   41.45     .06       0
   171.1    .045       0   186.1     .06       0  189.42    .016       0
  219.01     .06       0  337.39     .12       0
Bank Sta=171.1,186.1
XS Rating Curve= 0 ,0
Exp/Cntr=0.3,0.1

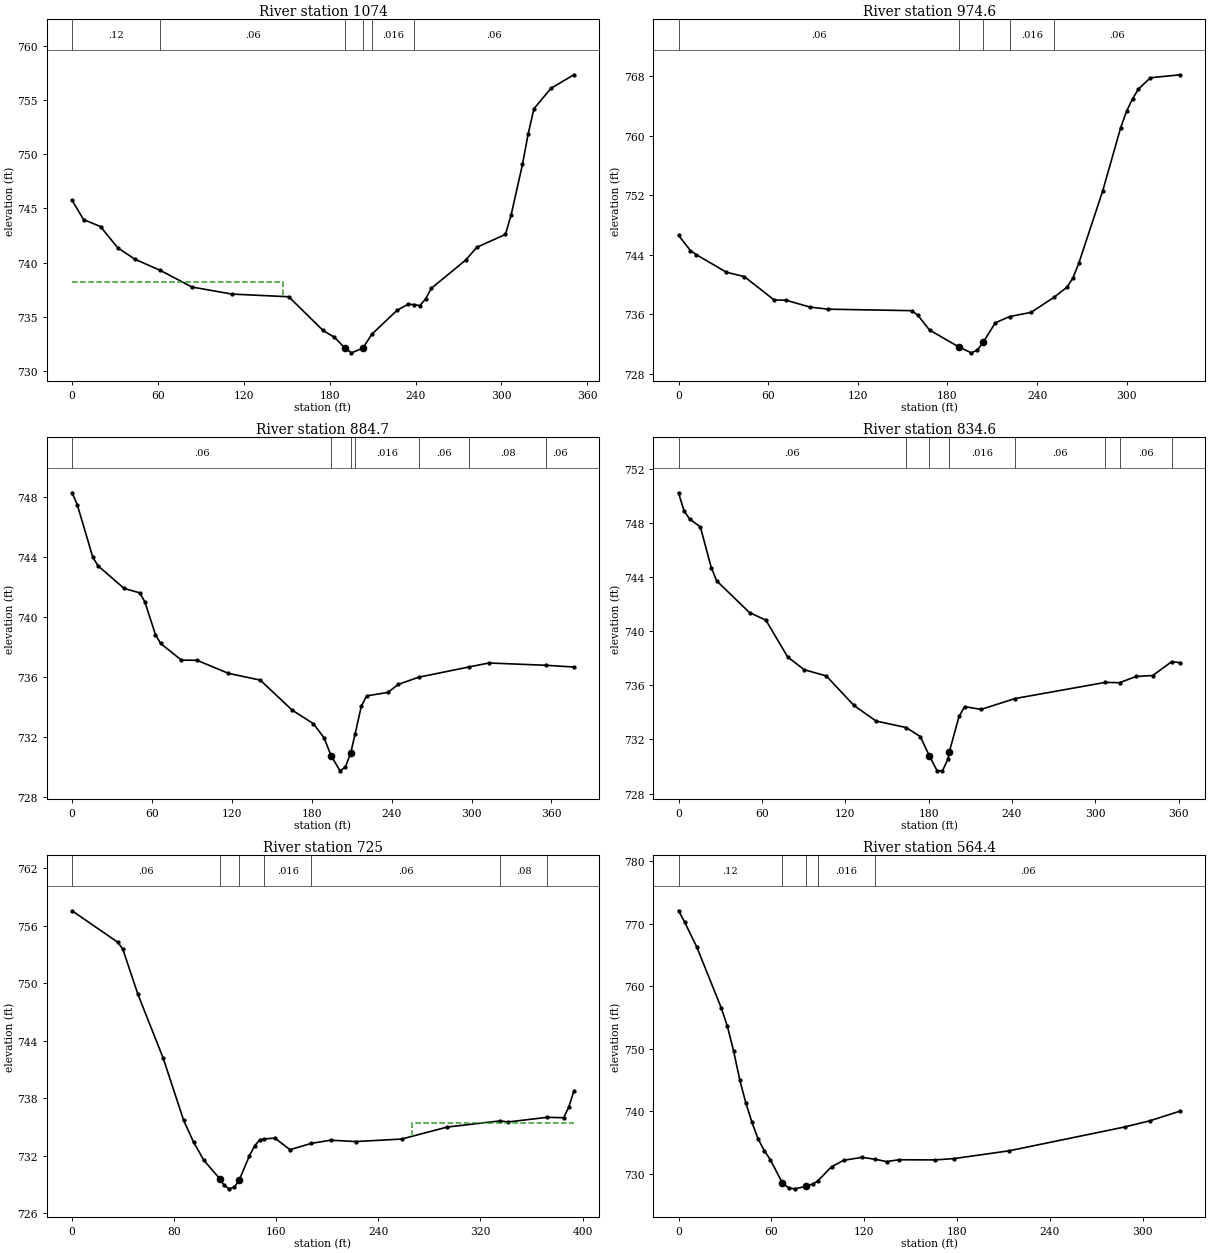
Type RM Length L Ch R = 1 ,1074    ,96.6,99.4,102.1
XS GIS Cut Line= 2
     1692683.846      368565.188     1692669.578      368915.488
#Sta/Elev= 30
       0  745.75       8  743.97    19.9  743.32    31.9  741.37    43.8  740.32
   61.62739.2847    83.7  737.75   111.6   737.1   151.4  736.85   175.3  733.75
   183.3  733.12   190.5  732.14   195.2  731.68   203.2  732.11  209.42733.3917
   227.1  735.61     235  736.17  238.98736.1202     243  736.04     247  736.65
     251  737.63   274.9  740.22   282.9  741.42   302.8   742.6   306.8  744.42
   314.7  749.05   318.7  751.89   322.7  754.19   334.6  756.07   350.6  757.32
#Mann= 6 ,-1 , 0
       0     .12       0   61.62     .06       0   190.5    .045       0
   203.2     .06       0  209.42    .016       0  238.98     .06       0
#XS Ineff= 2 , 0
          147.31   738.2
Permanent Ineff=
       F       F
Bank Sta=190.5,203.2
XS Rating Curve= 0 ,0
Exp/Cntr=0.3,0.1

Type RM Length L Ch R = 1 ,974.6   ,72.9,89.9,106.9
XS GIS Cut Line= 2
     1692610.199      368555.787     1692555.567      368887.251
#Sta/Elev= 30
       0  746.61       8  744.57      12  744.01      32  741.66      44  741.07
      64  737.93      72  737.89      88  736.97     100  736.69     156  736.49
     160  735.92     168  733.89     188  731.57     196  730.82     200  731.19
     204  732.26     212  734.85   221.6 735.696     236  736.26  251.54 738.316
     260  739.64     264  740.87     268   742.9     284  752.63   295.9  761.04
   299.9   763.3   303.9  764.97   307.9  766.29   315.9   767.8   335.9   768.2
#Mann= 5 ,-1 , 0
       0     .06       0     188    .045       0     204     .06       0
   221.6    .016       0  251.54     .06       0
Bank Sta=188,204
XS Rating Curve= 0 ,0
Exp/Cntr=0.3,0.1

Type RM Length L Ch R = 1 ,884.7   ,50.2,50.1,50.2
XS GIS Cut Line= 3
     1692584.946      368541.839     1692568.685      368654.066
      1692361.56       368816.85
#Sta/Elev= 30
       0  748.25     3.9  747.46    15.6  743.95    19.6  743.38    39.1  741.88
    50.8  741.59    54.7  740.98    62.6  738.81    66.5  738.22    82.1  737.11
    93.8   737.1   117.4  736.23   141.3  735.78   165.3  733.78   181.2  732.88
   189.2  731.94  194.46  730.76   201.2  729.74   205.2  729.99   209.2  730.92
  212.61732.2242   217.2  734.04   221.2  734.73   237.1  734.96   245.1   735.5
  260.41735.9745  298.33  736.66     313  736.92  356.01736.7656   376.8  736.65
#Mann= 7 ,-1 , 0
       0     .06       0  194.46    .045       0   209.2     .06       0
  212.61    .016       0  260.41     .06       0  298.33     .08       0
  356.01     .06       0
Bank Sta=194.46,209.2
XS Rating Curve= 0 ,0
Exp/Cntr=0.3,0.1

Type RM Length L Ch R = 1 ,834.6   ,115.7,109.6,103.2
XS GIS Cut Line= 3
     1692558.743      368522.973     1692545.861      368608.493
     1692329.789      368778.309
#Sta/Elev= 30
       0  750.22     3.9   748.9     7.9  748.29    15.7   747.7    23.6  744.68
    27.5  743.71    51.1  741.37    62.9  740.81    78.6  738.09    90.5  737.15
   106.4  736.69   126.3  734.51   142.2  733.36  163.86732.8802   174.1  732.21
  180.67  730.77   186.1   729.7     190  729.68     194  730.55  194.91  731.06
     202  733.71     206  734.42   217.9  734.22  242.39735.0229  307.26736.2136
  317.52736.1901   329.4  736.65   341.4  736.72  355.08737.7434   361.3  737.67
#Mann= 8 ,-1 , 0
       0     .06       0  163.86    .016       0  180.67    .045       0
  194.91    .016       0  242.39     .06       0  307.26     .08       0
  317.52     .06       0  355.08     .08       0
Bank Sta=180.67,194.91
XS Rating Curve= 0 ,0
Exp/Cntr=0.3,0.1

Type RM Length L Ch R = 1 ,725     ,160.4,160.6,160.9
XS GIS Cut Line= 2
     1692486.292      368477.049     1692249.708      368791.093
#Sta/Elev= 30
       0  757.54    35.7  754.27    39.7  753.56    51.6  748.83    71.5  742.14
    87.4   735.7    95.3   733.4   103.3  731.52     116  729.56   119.2   728.9
   123.1  728.55   127.1  728.72     131  729.48     139     732     143  733.03
     147  733.64  150.48 733.756   158.9  733.84   170.8  732.63  187.46733.2915
   202.6  733.62   222.4  733.48   258.2  733.74   293.9  734.99  335.37735.6323
   341.6  735.52  372.35736.0083   385.2  735.96   389.2  737.07   393.2  738.75
#Mann= 7 ,-1 , 0
       0     .06       0     116    .045       0     131     .06       0
  150.48    .016       0  187.46     .06       0  335.37     .08       0
  372.35     .06       0
#XS Ineff= 2 , 0
                          266.01          735.39
Permanent Ineff=
       F       F
Bank Sta=116,131
XS Rating Curve= 0 ,0
Exp/Cntr=0.3,0.1

Type RM Length L Ch R = 1 ,564.4   ,169.1,167.2,165.2
XS GIS Cut Line= 2
     1692340.143      368406.805     1692146.704      368667.175
#Sta/Elev= 30
       0  772.11       4  770.28    11.9  766.25    27.7  756.52    31.6  753.61
    35.6  749.67    39.6  745.04    43.5  741.36    47.5  738.24    51.4  735.63
    55.4  733.75    59.3   732.3    67.1  728.58    71.2  727.76    75.2  727.62
    82.1  728.01      87  728.41   90.07728.8935    98.9  731.15   106.8  732.19
   118.7  732.66  126.86732.3573   134.5  731.98   142.4  732.27   166.1  732.25
     178  732.46   213.6   733.7   288.8  737.54   304.6   738.5   324.4  740.07
#Mann= 5 ,-1 , 0
       0     .12       0    67.1    .045       0    82.1     .12       0
   90.07    .016       0  126.86     .06       0
Bank Sta=67.1,82.1
XS Rating Curve= 0 ,0
Exp/Cntr=0.3,0.1

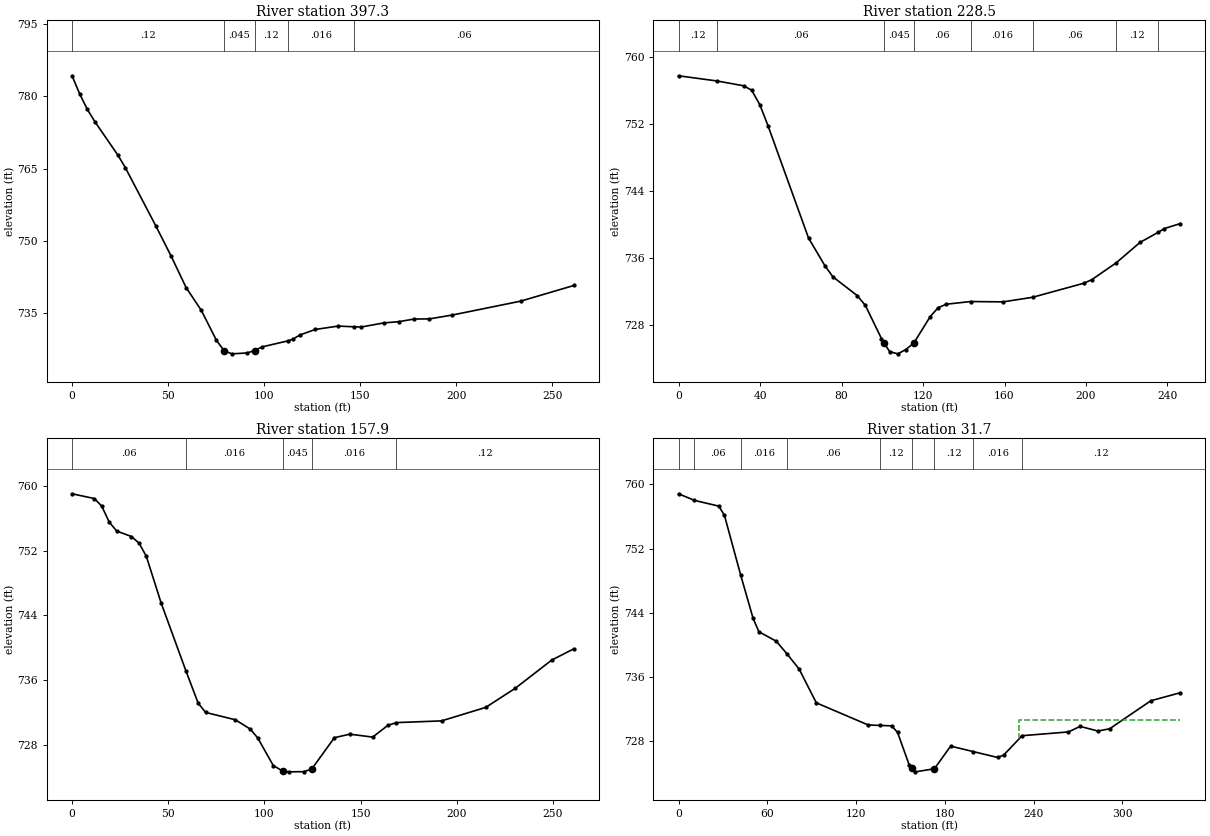
Type RM Length L Ch R = 1 ,397.3   ,187.3,168.7,150
XS GIS Cut Line= 2
     1692188.635      368324.423     1692051.536      368546.893
#Sta/Elev= 30
       0  784.25       4  780.46     7.9  777.31    11.9  774.71    23.8  767.83
    27.7  765.22    43.6  753.12    51.5  746.91    59.4  740.31    67.3  735.59
    75.2  729.36    79.2   727.2    83.2  726.57    91.1  726.75      95  727.24
      99  728.02  112.32729.2493   114.8  729.58   118.8  730.51   126.7  731.63
   138.6  732.33  147.01732.1736   150.5  732.13   162.3  732.98   170.2  733.25
   178.2  733.79   186.1  733.82     198  734.62   233.6   737.5   261.3  740.75
#Mann= 5 ,-1 , 0
       0     .12       0    79.2    .045       0      95     .12       0
  112.32    .016       0  147.01     .06       0
Bank Sta=79.2,95
XS Rating Curve= 0 ,0
Exp/Cntr=0.3,0.1

Type RM Length L Ch R = 1 ,228.5   ,69.7,70.6,70.3
XS GIS Cut Line= 4
     1691997.438      368255.235     1691970.425      368313.064
     1691993.863      368413.759      1691971.27      368489.571
#Sta/Elev= 30
       0  757.75   18.92757.1278    31.9  756.56    35.9  756.03    39.9   754.3
    43.9   751.8    63.8   738.4    71.8  735.11    75.8  733.76    87.7  731.53
    91.7  730.36    99.6   726.4   100.9  725.88   103.6  724.85   107.6  724.58
   111.5  725.08   115.5  725.87   123.5  729.01   127.4  730.08   131.4   730.5
  143.35730.8186   159.3  730.78  173.77 731.325   198.9     733   202.8  733.42
  214.88 735.446   226.5  737.87  235.41739.0715   238.4  739.52   246.3  740.12
#Mann= 8 ,-1 , 0
       0     .12       0   18.92     .06       0   100.9    .045       0
   115.5     .06       0  143.35    .016       0  173.77     .06       0
  214.88     .12       0  235.41     .06       0
Bank Sta=100.9,115.5
XS Rating Curve= 0 ,0
Exp/Cntr=0.3,0.1

Type RM Length L Ch R = 1 ,157.9   ,130.1,126.3,123.7
XS GIS Cut Line= 4
     1691946.164      368232.529     1691907.057      368316.536
     1691930.495      368417.231     1691914.412      368480.023
#Sta/Elev= 30
       0  759.02    11.6  758.43    15.4  757.51    19.3  755.53    23.2  754.42
    30.9  753.74    34.8  752.93    38.6  751.31    46.3  745.54   59.22737.1434
    65.6  733.15    69.5  732.02    84.9  731.12    92.7  729.96    96.6  728.85
   104.6  725.47   109.6  724.77   112.6  724.69   120.5  724.71   124.6  725.03
   136.4  728.91   144.4  729.34   156.3  728.98   164.2  730.43  168.62730.7684
   192.1  730.98   215.1  732.65   230.4     735   249.4  738.49   260.9  739.88
#Mann= 5 ,-1 , 0
       0     .06       0   59.22    .016       0   109.6    .045       0
   124.6    .016       0  168.62     .12       0
Bank Sta=109.6,124.6
XS Rating Curve= 0 ,0
Exp/Cntr=0.3,0.1

Type RM Length L Ch R = 1 ,31.7    ,31.6,31.7,31.8
XS GIS Cut Line= 3
     1691814.303      368173.631     1691773.813      368290.992
     1691857.406      368489.017
#Sta/Elev= 30
       0  758.83   10.73758.0087    27.2  757.29      31  756.15   41.98748.7026
    50.4  743.28    54.3  741.62      66  740.44   73.22738.8784    81.5  736.96
    93.1  732.75   128.1  729.99  136.01729.9302     144  729.88     148  729.06
     156  724.94   157.9  724.56     160  724.14   172.9  724.52   183.9  727.35
  199.29726.6589   215.7  725.93   219.7  726.23  232.18728.6474   263.5  729.12
   271.4  729.81   283.4  729.23   291.3  729.51   319.2  733.01   339.1  734.01
#Mann= 9 ,-1 , 0
       0     .12       0   10.73     .06       0   41.98    .016       0
   73.22     .06       0  136.01     .12       0   157.9    .045       0
   172.9     .12       0  199.29    .016       0  232.18     .12       0
#XS Ineff= 2 , 0
                          230.02          730.62
Permanent Ineff=
       F       F
Bank Sta=157.9,172.9
XS Rating Curve= 0 ,0
Exp/Cntr=0.3,0.1
LCMann Table=0

Chan Stop Cuts=-1
Use User Specified Reach Order=0
Composite Channel Slope=5